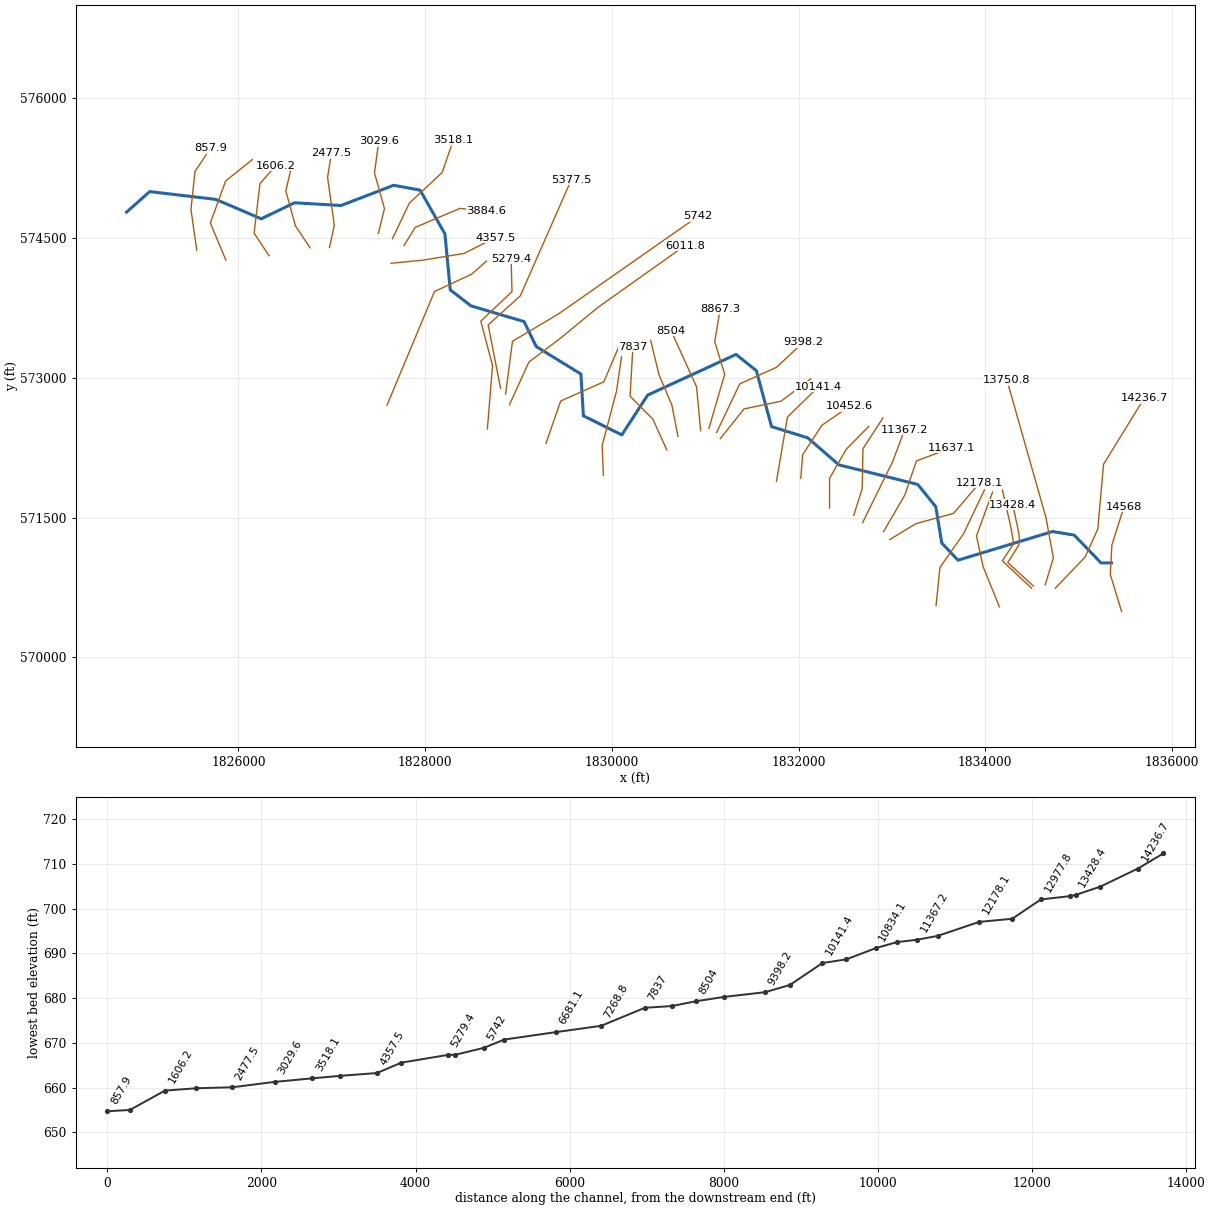
--- GreenCrk.prj (project) ---

Proj Title=GreenCrk
Current Plan=p01
Default Exp/Contr=0,0
English Units
Geom File=g01
Flow File=f01
Plan File=p01
BEGIN DESCRIPTION:
AMEC Environment & Infrastructure, 2013
Projection: NAD 1983 State Plane West Virginia South FIPS 4702 (US Feet)
Vertical Datum: NAVD 1988
END DESCRIPTION:
DSS Export Rating Curves= 0
DSS Export Rating Curve Sorted= 0
DSS Export Volume Flow Curves= 0
DXF OffsetX= 0
DXF OffsetY= 0
DXF ScaleX= 0
DXF ScaleY= 0

--- GreenCrk.p01 (plan) ---

Plan Title=Floodplain
Program Version=4.00
Geom File=g01
Flow File=f01
K Sum by GR=0
Std Step Tol=0.01
Critical Tol=0.01
Num of Std Step Trials=20
Max Error Tol=0.3
Flow Tol Ratio=0.001
Split Flow NTrial=30
Split Flow Tol=0.02
Split Flow Ratio=0.02
Log Output Level=0
Friction Slope Method=1
Unsteady Friction Slope Method=2
Unsteady Bridges Friction Slope Method=1
Global Log Level=0
CheckData=False
Run HTab=0
Run UNet=0
Run PostProcess=0
UNET Theta=0
UNET Theta Warmup=0
UNET ZTol=0
UNET ZSATol=0
UNET MxIter=0
UNET MaxInSteps=0
UNET DtIC=0
UNET DtMin=0
UNET MaxCRTS=0
UNET WFStab=0
UNET SFStab=0
UNET WFX=0
UNET SFX=0
UNET DSS MLevel=0
UNET DZMax Abort=0
UNET Convert EG Bridges=0
UNET Use Existing IB Tables=0
UNET Froude Limit=0
UNET Froude Power=0
Write IC File=0
Echo Input=False
Echo Output=False
Write Detailed=0

--- GreenCrk.f01 (steady flow) ---

Flow Title=NFF Regression Equation
Program Version=4.10
Number of Profiles= 1
Profile Names=P100yr
River Rch & RM=GreenCrk,Main            ,14568
895.2651
River Rch & RM=GreenCrk,Main            ,13750.8
1946.901
River Rch & RM=GreenCrk,Main            ,5377.5
2110.412
River Rch & RM=GreenCrk,Main            ,5279.4
2816.234
River Rch & RM=GreenCrk,Main            ,4673.7
2817.554
River Rch & RM=GreenCrk,Main            ,4357.5
 3254.73
River Rch & RM=GreenCrk,Main            ,432.7
3328.574
River Rch & RM=GreenCrk,Main            ,45.6
3385.704
Boundary for River Rch & Prof#=GreenCrk,Main            , 1
Up Type= 0
Dn Type= 3
Dn Slope=0.006
DSS Import GetInterval= 0
DSS Import GetPeak= 0
DSS Import FillOption= 0

--- GreenCrk.g01 (geometry) ---

Geom Title=USGS 3m DEM
Program Version=4.10

River Reach=GreenCrk        ,Main
Reach XY= 30
     1835351.418      571012.557     1835241.199      571012.791
     1834953.705      571311.249     1834720.989      571349.446
     1833708.518       571042.01     1833534.842       571226.09
     1833470.568      571615.104     1833277.786      571854.757
     1832432.014      572064.858     1832098.559      572354.869
     1831711.274      572474.683        1831548.      573075.567
     1831330.907      573249.225     1830384.124      572813.427
     1830106.587      572386.041     1829694.985       572590.95
     1829668.602      573039.163     1829189.266      573334.376
     1829059.288      573601.928     1828491.101      573770.251
     1828268.799      573942.172     1828211.461       574543.06
     1827945.728      575011.951     1827662.646      575064.038
     1827098.236      574846.927     1826601.545      574876.427
     1826243.798       574704.48     1825755.759      574912.858
      1825048.95      574996.185     1824800.656      574776.222

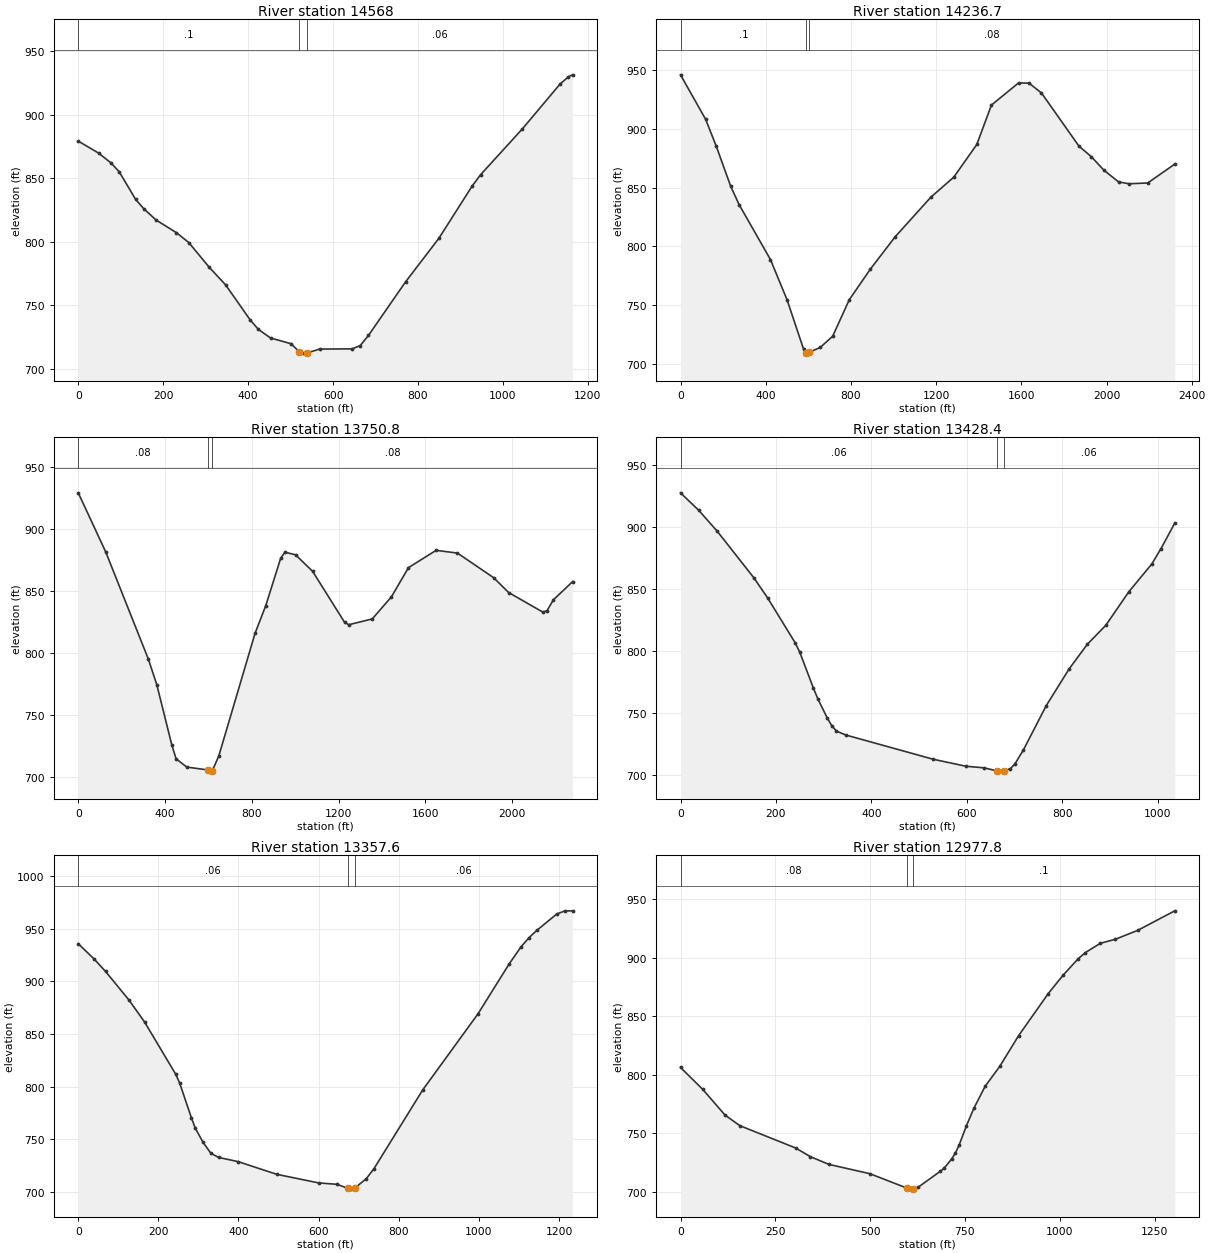
Type RM Length L Ch R = 1 ,14568   ,339.4,331.1,322.9
XS GIS Cut Line= 4
      1835461.38      570491.684     1835340.301      570887.965
     1835357.258      571204.498     1835487.387      571616.915
#Sta/Elev= 30
       0  879.37    48.2  869.84    77.1  862.15    96.4  855.23   134.9  833.55
   154.2  826.11   183.1  817.23   231.3   807.2   260.2  799.44   308.4  779.95
   346.9  766.13   404.7  738.53     424  731.06   452.8  724.23   500.8  719.76
     520  713.57   529.6  712.32   539.2   712.5   568.1   715.5   644.9  715.69
   664.1   718.3   683.3  726.24   770.7  768.48   849.3  802.85   927.9  844.15
   947.6  852.97  1045.9  889.05  1134.3  924.24    1154  929.99  1163.8  931.57
#Mann= 3 , 0 , 0
       0      .1       0     520    .045       0   539.2     .06       0
Bank Sta=520,539.2
XS Rating Curve= 0 ,0
Exp/Cntr=0.3,0.1

Type RM Length L Ch R = 1 ,14236.7 ,472.4,486,499.5
XS GIS Cut Line= 5
     1834750.871       570741.85     1835070.034      571075.139
     1835206.167      571376.636     1835267.993      572070.912
     1835703.396      572778.936
#Sta/Elev= 30
       0  946.28   117.8  908.41   166.9  885.85   235.6  851.27   274.9  835.64
   422.2  788.77   500.4  754.34   578.2   712.1   589.2  709.13   597.7  708.93
   604.2  709.65     656  713.78   714.4  723.35   792.3  754.44   890.4  780.34
  1008.2  808.24  1175.1  841.86  1283.1  859.03  1391.1  886.89  1459.8  920.48
  1587.1  939.39    1636  939.21  1694.6  930.85  1870.7  885.45  1929.3  876.38
    1988   864.9  2056.4  855.01  2105.4  853.38  2193.4  854.03  2320.5  870.15
#Mann= 3 , 0 , 0
       0      .1       0   589.2    .045       0   604.2     .08       0
Bank Sta=589.2,604.2
XS Rating Curve= 0 ,0
Exp/Cntr=0.3,0.1

Type RM Length L Ch R = 1 ,13750.8 ,324.5,322.5,320.6
XS GIS Cut Line= 4
     1834642.415      570775.895     1834730.612      571066.207
     1834650.223      571501.649      1834232.57      572975.443
#Sta/Elev= 30
       0  929.17   127.2  881.32   323.1  795.17   362.4  774.31   431.3  725.89
     451  714.84   500.2  708.18   598.6  705.83   608.4  704.91   618.3  705.37
   647.8  717.18     815  816.04     864  838.14   932.8  876.36   952.4  881.33
  1001.5  879.23  1080.1  865.94  1227.4  824.85    1247   822.9    1355  827.56
  1443.4  845.37    1522   868.9  1649.6  882.84  1747.8  880.61  1914.7  860.75
  1983.5  848.84  2140.6  833.12  2160.2   834.1  2189.7  842.91    2278  857.56
#Mann= 3 , 0 , 0
       0     .08       0   598.6    .045       0   618.3     .08       0
Bank Sta=598.6,618.3
XS Rating Curve= 0 ,0
Exp/Cntr=0.3,0.1

Type RM Length L Ch R = 1 ,13428.4 ,76.4,70.6,72.4
XS GIS Cut Line= 6
     1834517.584      570763.801      1834241.56      571017.216
     1834355.549       571197.15     1834368.738      571244.253
     1834359.318      571334.691     1834296.199      571636.151
#Sta/Elev= 30
       0  927.32    38.4  913.16    76.9  896.39   153.7  858.83   182.6  842.59
   240.2  806.49   249.8  798.96   278.6  769.79   288.2  760.93   307.5  745.83
   317.1   739.5   326.7  735.34   345.9  732.19   529.6   712.6   597.5  707.01
   636.6  705.67   662.4  703.26     673  703.04   677.4  703.23   691.2  705.03
   700.3  708.63   718.5  720.13     766  755.61   814.2   785.4   852.7  805.39
   891.2   820.6   939.3  847.55   987.4  869.94  1006.7  882.34  1035.6  902.94
#Mann= 3 , 0 , 0
       0     .06       0   662.4    .045       0   677.4     .06       0
Bank Sta=662.4,677.4
XS Rating Curve= 0 ,0
Exp/Cntr=0.3,0.1

Type RM Length L Ch R = 1 ,13357.6 ,371.4,379.7,380.4
XS GIS Cut Line= 6
     1834496.601      570741.976     1834184.094      571035.115
     1834293.373      571202.802      1834300.91      571246.137
     1834271.601       571411.05     1834184.533      571794.962
#Sta/Elev= 30
       0   935.6      39   921.4    68.2   909.3   126.6   882.2   165.6  861.33
   243.4  811.74   253.2  803.39   282.4  770.52   292.1  760.64   311.6  747.15
   331.1  736.74   350.6  732.84   399.3  728.85   495.2  716.86     600  708.69
   646.2  707.33   672.6  703.56  681.66  702.78   691.2  704.04   719.1  712.76
   737.8  721.96   859.8  796.88   997.6  868.96  1076.3  916.85  1105.8  932.96
  1125.5  941.49  1145.2  948.47  1194.4  963.82  1214.1  966.71  1233.8  966.85
#Mann= 3 , 0 , 0
       0     .06       0   672.6    .045       0   691.2     .06       0
Bank Sta=672.6,691.2
XS Rating Curve= 0 ,0
Exp/Cntr=0.3,0.1

Type RM Length L Ch R = 1 ,12977.8 ,390.9,372.2,353.5
XS GIS Cut Line= 4
     1834152.256      570541.443     1833975.846      570976.885
     1833906.622      571302.908     1834078.848      571772.519
#Sta/Elev= 30
       0  806.22    58.7  787.42   117.4  765.42   156.6  756.35   303.4  737.28
   342.6  729.81   391.5   723.2   499.2  715.27   596.9  702.94   607.1  702.04
   611.9  702.16   626.7  703.67   685.5  717.42   695.3  720.02   714.9  727.84
   724.7  732.83   734.5  739.64   754.1  756.37   773.7  771.36   803.1  789.95
   842.3  807.35   891.4  833.36   969.8   869.5  1009.1  885.28  1048.3  899.15
  1067.9   904.6  1107.2  912.49  1146.4  915.91  1205.2   923.5  1303.3  940.28
#Mann= 3 , 0 , 0
       0     .08       0   596.9    .045       0   611.9      .1       0
Bank Sta=596.9,611.9
XS Rating Curve= 0 ,0
Exp/Cntr=0.3,0.1

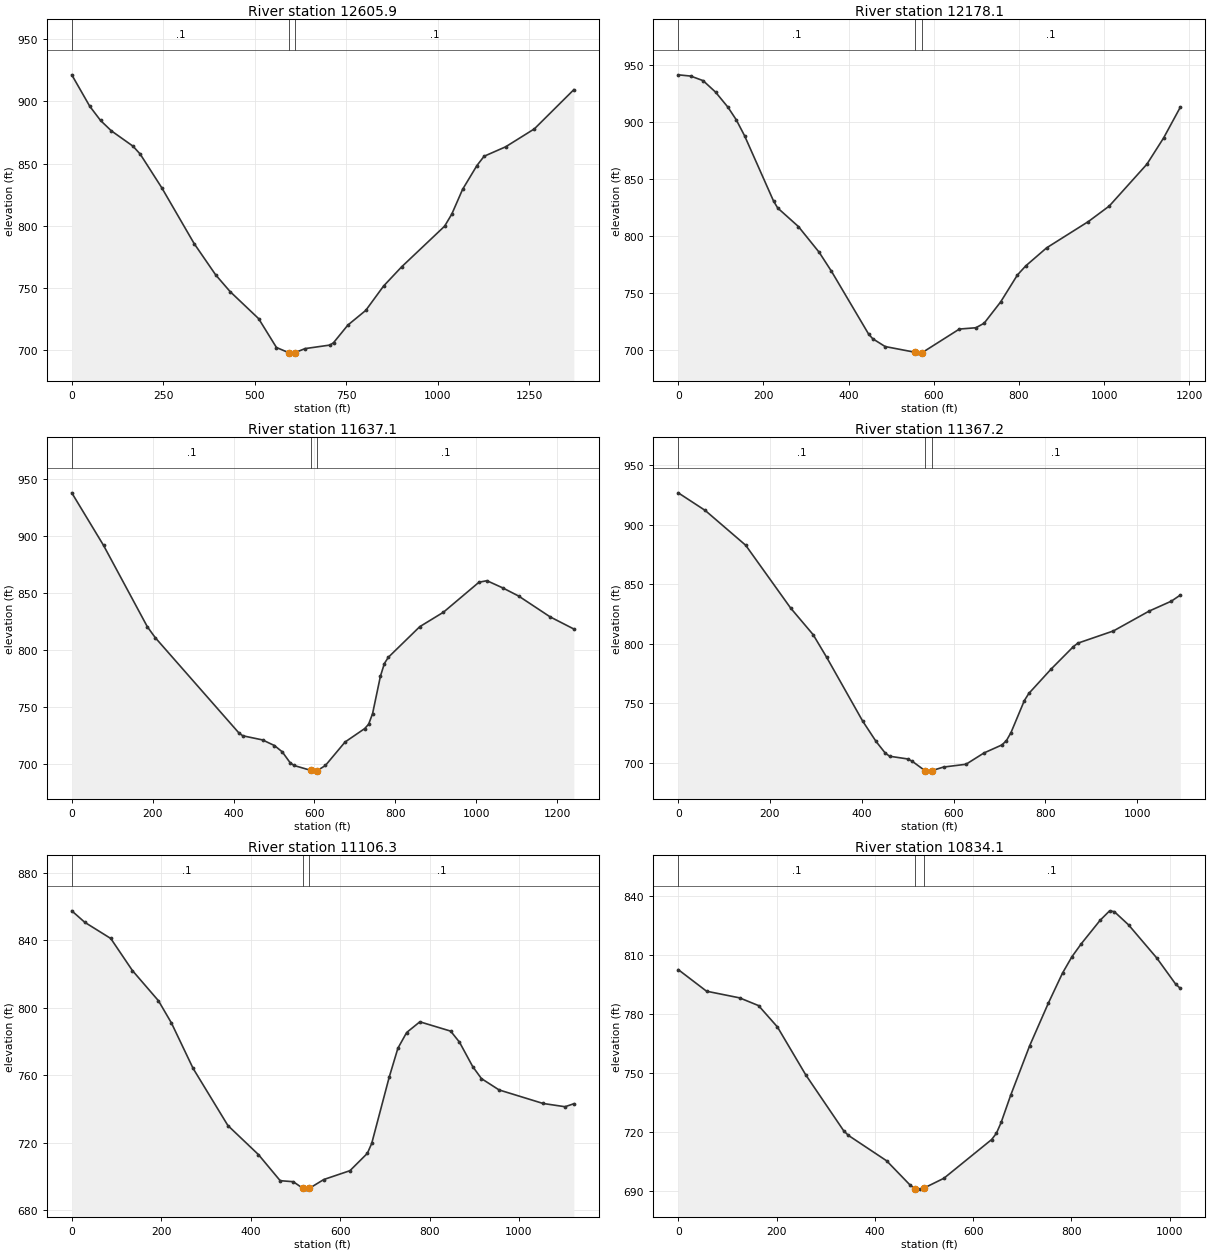
Type RM Length L Ch R = 1 ,12605.9 ,442.8,427.4,412
XS GIS Cut Line= 4
     1833473.413      570554.841     1833515.841       570965.72
     1833768.174      571325.239     1833991.499      571794.841
#Sta/Elev= 30
       0  921.27    49.2     896    78.7  884.59   108.2  876.28   167.2  863.99
   186.9  857.66   245.9  830.59   334.4  785.76   393.4  760.56   432.6  747.21
   510.7  725.43   559.5  702.23   594.4  697.91   598.5  697.72   609.4  698.03
   637.6  701.35   705.9  704.21   715.6  706.14   754.7  720.27   803.5  732.03
   852.3  751.63   901.4  766.97  1019.1  799.71  1038.7   809.4  1068.2  829.27
  1107.4   848.4    1127  855.86  1185.9  863.45  1264.4  877.86  1372.3  909.36
#Mann= 3 , 0 , 0
       0      .1       0   594.4    .045       0   609.4      .1       0
Bank Sta=594.4,609.4
XS Rating Curve= 0 ,0
Exp/Cntr=0.3,0.1

Type RM Length L Ch R = 1 ,12178.1 ,519.1,540.9,562.8
XS GIS Cut Line= 4
     1832976.504      571262.477     1833259.042      571434.658
     1833660.988      571544.076     1833940.393      571873.145
#Sta/Elev= 30
       0  941.07    29.2  939.98    58.4  935.97    87.6  925.94   116.8  912.66
   136.2  901.66   155.7  887.72   223.8  830.43   233.6  824.29   282.2  808.04
   330.9  785.49   359.9  768.78   447.1  713.72   456.8  709.64   485.9  702.81
   557.2   697.7   563.4  697.03   572.2  697.31   660.2  718.13     699  719.28
   718.4  723.26   757.2  741.95   796.5  765.53   816.1  773.53   865.2  789.37
   963.3  812.44  1012.3  826.03  1100.6  862.69  1139.9  885.74  1179.1   912.7
#Mann= 3 , 0 , 0
       0      .1       0   557.2    .045       0   572.2      .1       0
Bank Sta=557.2,572.2
XS Rating Curve= 0 ,0
Exp/Cntr=0.3,0.1

Type RM Length L Ch R = 1 ,11637.1 ,272.5,269.9,267.2
XS GIS Cut Line= 4
     1832910.562      571347.903     1833137.595      571739.209
     1833263.508      572106.801     1833638.037      572248.869
#Sta/Elev= 30
       0  937.69    78.7  891.57   186.9  820.35   206.5  810.78   413.1   727.4
   422.9  724.85   471.8  721.22     501  716.32   520.4  710.82   539.8  701.32
   549.5  698.85   590.9  694.57  598.96  693.89   605.9  694.04   627.2  698.84
   675.8   719.4   724.4  731.18   734.1  735.02   743.8  744.24   763.2  777.02
     773  788.13   782.7  793.59   860.5  820.44   919.1  833.12    1007  859.39
  1026.6   860.7  1065.7  854.41  1104.8  847.31  1182.9  829.02  1241.5  818.39
#Mann= 3 , 0 , 0
       0      .1       0   590.9    .045       0   605.9      .1       0
Bank Sta=590.9,605.9
XS Rating Curve= 0 ,0
Exp/Cntr=0.3,0.1

Type RM Length L Ch R = 1 ,11367.2 ,250.6,260.9,271.1
XS GIS Cut Line= 3
     1832686.391      571444.975     1833006.709      572095.636
     1833136.261      572441.185
#Sta/Elev= 30
       0  926.89    58.8  912.08     147  882.85     245  830.06     294  807.73
   323.4  788.74   401.8  735.21   431.2  717.95   450.8  708.39   460.6  705.55
   499.8  703.28   509.6  701.42   538.4  693.26   548.8  693.03   553.4  693.51
   578.2  696.45   627.2  698.79   666.4   708.3   705.6  715.07   715.4  718.73
   725.2  725.38   754.4  752.34   764.1  758.29   812.6  778.75   861.2  797.63
   870.9  800.55   948.6  810.85  1026.3   827.5  1074.8  835.86  1094.3  840.96
#Mann= 3 , 0 , 0
       0      .1       0   538.4    .045       0   553.4      .1       0
Bank Sta=538.4,553.4
XS Rating Curve= 0 ,0
Exp/Cntr=0.3,0.1

Type RM Length L Ch R = 1 ,11106.3 ,283.8,272.1,260.5
XS GIS Cut Line= 4
     1832591.847      571523.318     1832682.285      571809.705
     1832690.658      572238.448      1832905.03      572568.379
#Sta/Elev= 30
       0  857.32    29.1  850.52    87.2  840.94   135.6  821.95   193.8  804.07
   222.8  790.93   271.3     764   349.1  730.16   417.3  712.98     466   697.5
   495.2   696.9   515.9  693.13   524.5   692.5   530.9  692.92   563.5  698.19
     622  703.43   660.9  713.69   670.7  719.62   709.7  758.75   729.2  775.95
   748.8  785.26   778.3  791.59   847.2  786.07   866.9  779.54   896.4  765.11
     916  757.96   955.4  751.25  1053.8  743.23  1102.9   741.3  1122.6  743.07
#Mann= 3 , 0 , 0
       0      .1       0   515.9    .045       0   530.9      .1       0
Bank Sta=515.9,530.9
XS Rating Curve= 0 ,0
Exp/Cntr=0.3,0.1

Type RM Length L Ch R = 1 ,10834.1 ,382.8,381.5,380.1
XS GIS Cut Line= 4
     1832332.332      571602.135     1832332.332      571919.226
      1832510.51      572231.159     1832752.143      572477.485
#Sta/Elev= 30
       0  802.76    57.6  791.78   124.9  788.39   163.4  784.46   201.8   773.6
   259.4  749.26   336.5  720.86   346.2  718.47   423.9  705.57   472.4  693.04
   482.1  691.38   491.8  691.16   499.4  691.63   540.4  696.67   637.5  716.35
   647.2  719.52   656.9  725.05   676.3  738.88   714.7  763.92     753  785.74
   781.8  801.01   800.9   809.3   820.1  815.96   858.4  827.87   877.6  832.64
   887.2   832.2     916  825.54   973.5  808.67  1011.8  795.43  1021.4  793.22
#Mann= 3 , 0 , 0
       0      .1       0   482.1    .045       0   499.4      .1       0
Bank Sta=482.1,499.4
XS Rating Curve= 0 ,0
Exp/Cntr=0.3,0.1

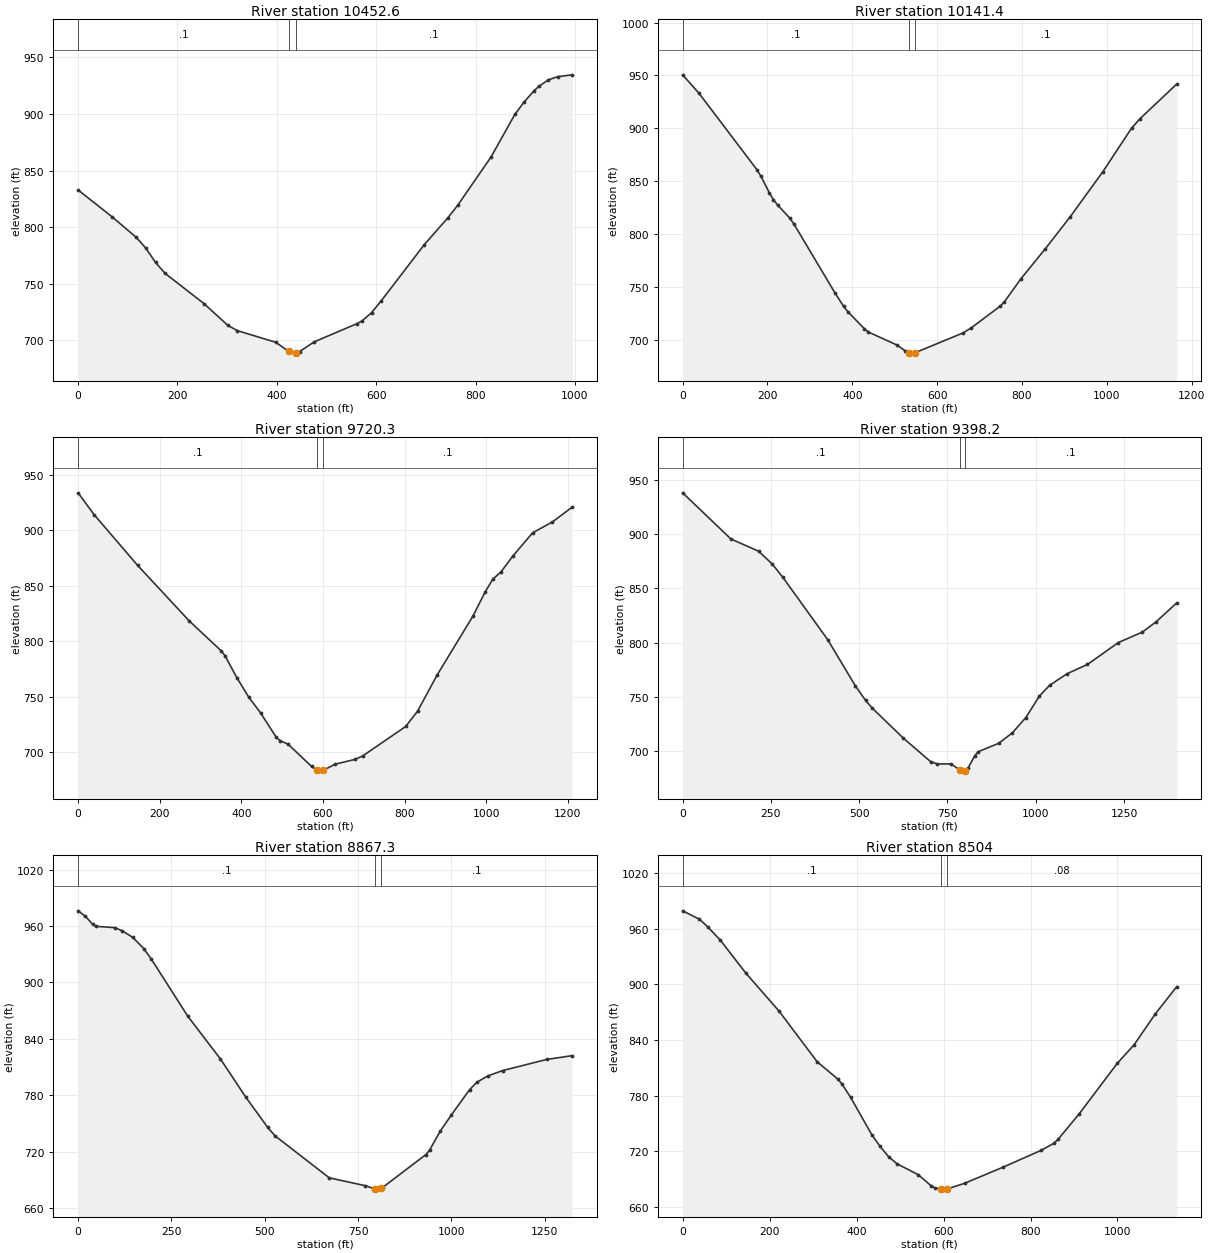
Type RM Length L Ch R = 1 ,10452.6 ,301.8,311.1,320.3
XS GIS Cut Line= 4
     1832024.173      571921.459      1832044.27      572173.792
      1832249.71       572488.65     1832550.244      572696.313
#Sta/Elev= 30
       0  832.83    68.2  809.19   116.8  791.04   136.3  781.46   155.8  768.78
   175.2  759.08   253.1  732.51   301.3   713.2   320.6  708.51   397.7  698.26
   423.8  690.17   436.3  688.66   438.8  689.02   445.9  690.05   474.8  698.54
   561.6  714.78   571.2  717.06   590.5  724.38   609.8   734.7   696.4  784.35
   744.4  808.37   763.7  819.14     831  861.94     879   899.6   898.2  910.88
   917.5  920.48   927.1  924.33   946.3  930.14   965.6  933.04   994.4  934.62
#Mann= 3 , 0 , 0
       0      .1       0   423.8    .045       0   438.8      .1       0
Bank Sta=423.8,438.8
XS Rating Curve= 0 ,0
Exp/Cntr=0.3,0.1

Type RM Length L Ch R = 1 ,10141.4 ,494.8,421.1,390.9
XS GIS Cut Line= 3
     1831763.435      571887.751     1831881.259      572577.972
     1832213.543      572902.456
#Sta/Elev= 30
       0  950.62    38.9  933.04     175  861.11   184.8  854.77   204.2  839.36
     214  832.74   223.7  827.79   252.8  815.19   262.6  809.58   359.8  744.19
   379.3  732.12     389  727.12   427.9  711.06   437.6  707.78   505.7   695.4
   525.2  689.83   533.1  688.33   544.6  687.83   548.1  688.24   661.3  706.95
   680.8  711.83   748.6  732.19   758.3  736.21     797  757.82     855  786.41
   913.1  816.31   990.5   859.1  1058.2  900.22  1077.6  908.99  1164.6  941.88
#Mann= 3 , 0 , 0
       0      .1       0   533.1    .045       0   548.1      .1       0
Bank Sta=533.1,548.1
XS Rating Curve= 0 ,0
Exp/Cntr=0.3,0.1

Type RM Length L Ch R = 1 ,9720.3  ,317.2,322.1,373.1
XS GIS Cut Line= 4
     1831161.572      572345.999     1831416.787       572665.06
     1831812.035      572747.682     1832130.648      572986.884
#Sta/Elev= 30
       0  933.75    38.9   914.2   145.9  868.34   272.4  818.28   350.2  791.54
   359.9     787   389.1  767.07   418.2  749.59     447  735.51   485.5  713.51
   495.1  710.32   514.3  707.31     572  687.22   585.7  683.57   591.2  682.94
   600.7  683.66   629.7   689.2   677.8  693.45     697  696.52   802.8  723.18
   831.8  736.94   880.4  769.91   967.8  822.78     997  844.07  1016.4     856
  1035.9   862.3    1065  876.59  1113.6  897.66  1162.2  907.47  1210.8  920.88
#Mann= 3 , 0 , 0
       0      .1       0   585.7    .045       0   600.7      .1       0
Bank Sta=585.7,600.7
XS Rating Curve= 0 ,0
Exp/Cntr=0.3,0.1

Type RM Length L Ch R = 1 ,9398.2  ,498.1,530.8,563.5
XS GIS Cut Line= 4
     1831122.481      572412.044     1831369.894      572933.024
     1831765.141      573111.667     1832048.736      573377.399
#Sta/Elev= 30
       0   938.3   136.8  895.66   215.1   884.4   254.2  872.44   283.5   860.4
   410.6  802.83   488.8  760.18   518.1   746.6   537.6  739.29   624.9   711.8
     702  690.14   721.3  687.88   759.9  688.01   784.2  682.57   798.4  681.32
   799.2  681.55   808.1  684.09   827.4  695.56     837  699.26   894.8  706.95
   933.4  716.58   971.9  730.79  1010.5  750.72  1039.6  760.66  1088.2  771.17
  1146.5  779.85    1234  800.06    1302  809.74  1340.8  819.19  1399.1  836.66
#Mann= 3 , 0 , 0
       0      .1       0   784.2    .045       0   799.2      .1       0
Bank Sta=784.2,799.2
XS Rating Curve= 0 ,0
Exp/Cntr=0.3,0.1

Type RM Length L Ch R = 1 ,8867.3  ,360.3,363.3,366.2
XS GIS Cut Line= 4
     1831040.227      572456.289     1831209.115      573037.977
     1831101.929      573386.331     1831160.627      573734.614
#Sta/Elev= 30
       0  976.13    19.5  970.28    39.1  961.82    48.8   959.6    97.7  958.28
   117.2  955.09   146.5  947.86   175.8  935.98   195.4  925.24   293.1  864.47
     381  818.76   449.4   777.9     508  745.79   527.6  736.88   672.8  692.25
   768.8  683.97   795.4  680.46   797.5  680.27   810.4  681.14   816.7  682.37
   931.8  717.06   941.4  721.68   970.2  742.08   999.6  759.02  1048.7  786.05
  1068.3  793.98  1097.7  800.65    1137   806.3  1254.7  818.09  1323.4  822.16
#Mann= 3 , 0 , 0
       0      .1       0   795.4    .045       0   810.4      .1       0
Bank Sta=795.4,810.4
XS Rating Curve= 0 ,0
Exp/Cntr=0.3,0.1

Type RM Length L Ch R = 1 ,8504    ,320.4,319.9,319.4
XS GIS Cut Line= 3
     1830951.408      572430.329     1830907.655      572901.762
     1830633.801      573505.218
#Sta/Elev= 30
       0  979.39    38.6  970.37      58  962.03      87  947.58   144.9   912.5
   222.2  870.98   309.2  816.72   357.5  797.72   367.2  792.14   386.5  778.12
   434.8  738.15   454.1  725.33   473.5  714.37     493  706.61   541.7  694.91
   570.9  683.17   580.7  680.57   593.6  679.48   600.2  679.31   608.6  679.47
   648.9  685.66   736.6  702.92   824.3  721.09   853.5  728.63   863.3  732.94
     912  760.51   999.7  815.03  1038.7  835.21  1087.4   868.5  1136.2  897.59
#Mann= 3 , 0 , 0
       0      .1       0   593.6    .045       0   608.6     .08       0
Bank Sta=593.6,608.6
XS Rating Curve= 0 ,0
Exp/Cntr=0.3,0.1

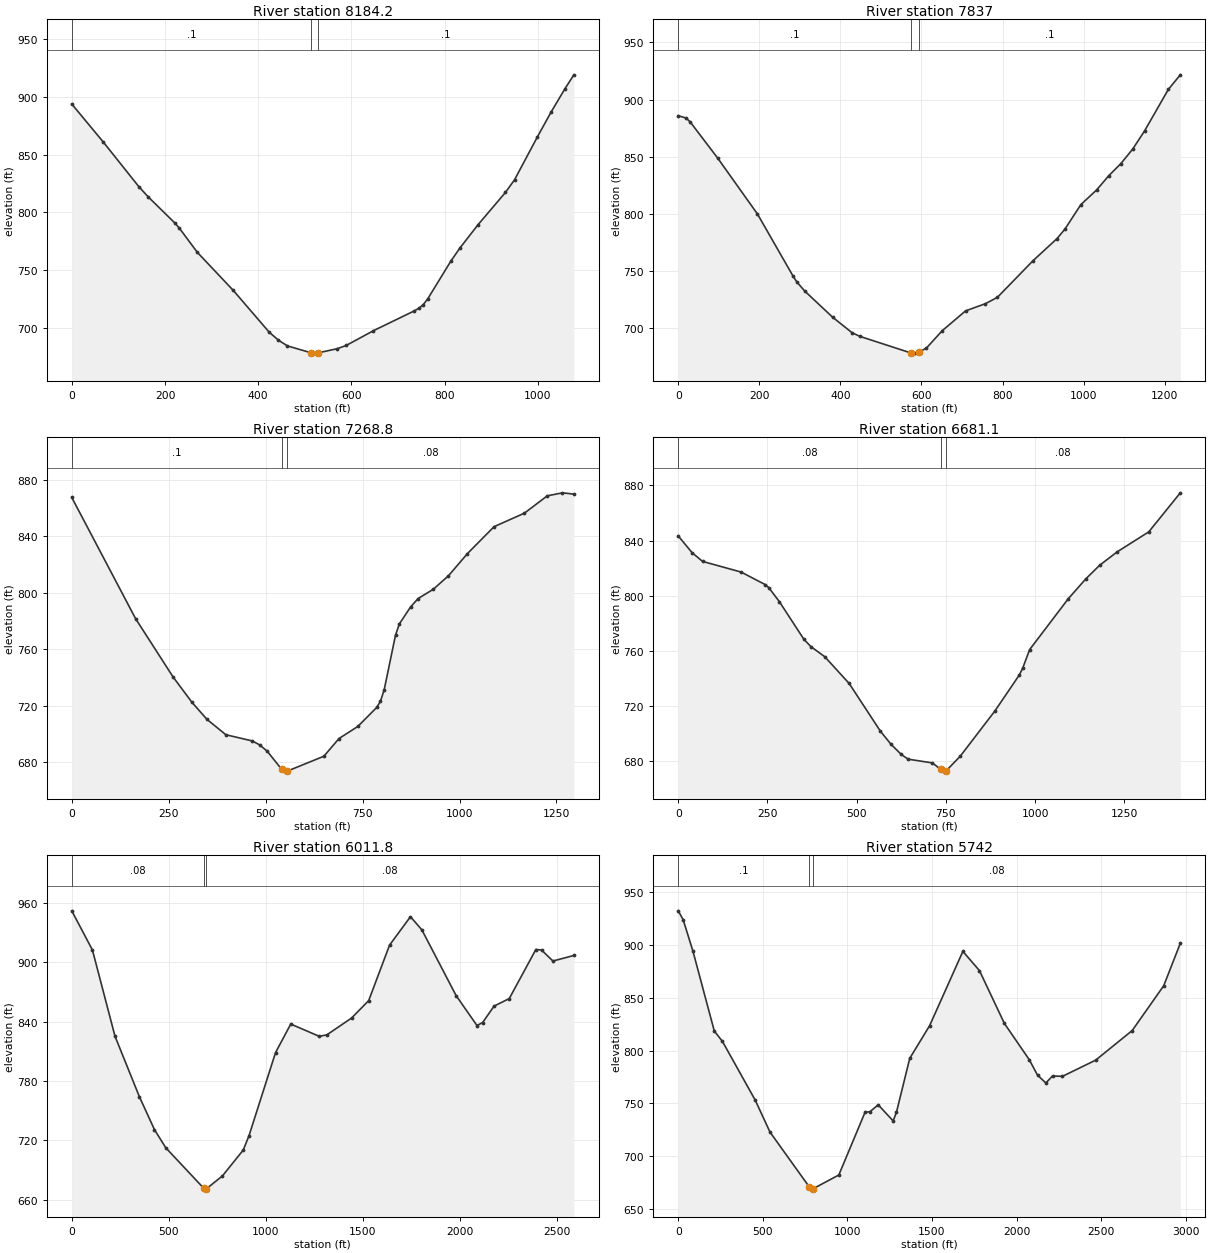
Type RM Length L Ch R = 1 ,8184.2  ,338.2,346.7,355.2
XS GIS Cut Line= 4
     1830708.915      572368.066     1830642.407      572708.025
     1830505.709      573029.045     1830415.714       573399.94
#Sta/Elev= 30
       0  893.66    67.4   860.9   144.3  821.99   163.6  813.51   221.3   790.7
   230.9  786.25   269.4  765.36   346.4  732.49   423.9  696.16   443.3  689.44
   462.7  684.45     513  678.56   520.9  678.22     528  678.41   569.3  682.05
   588.7  684.85   646.9  697.58   734.5  714.71   744.2  716.88     754  720.16
   763.8  725.32   812.8  757.55   832.3  768.98   871.5  789.29   930.2  817.17
   949.8  828.15   998.7  865.16    1028  886.56  1057.4  906.55    1077  918.92
#Mann= 3 , 0 , 0
       0      .1       0     513    .045       0     528      .1       0
Bank Sta=513,528
XS Rating Curve= 0 ,0
Exp/Cntr=0.3,0.1

Type RM Length L Ch R = 1 ,7837    ,592.1,567.9,543.7
XS GIS Cut Line= 4
     1830588.331      572225.152     1830440.003      572554.667
     1830195.317      572801.275     1830225.518      573330.159
#Sta/Elev= 30
       0  885.84    19.5  883.74    29.3  880.45    97.7   848.5   195.3  799.78
   283.2  745.34     293  739.97   312.5  732.06   380.7  709.36   428.9  695.68
   448.2  692.51   573.7  678.02   583.3  677.84     593  678.56   612.3   682.3
   650.9  697.39   708.8  714.85   757.8  721.16   787.2  726.69   875.5  758.92
   934.4  778.18     954  786.55   993.2  807.94  1032.5  820.95  1061.9  833.22
  1091.4  843.71  1120.8  856.46  1150.2  872.43  1209.1  908.91  1238.5  921.63
#Mann= 3 , 0 , 0
       0      .1       0   573.7    .045       0     593      .1       0
Bank Sta=573.7,593
XS Rating Curve= 0 ,0
Exp/Cntr=0.3,0.1

Type RM Length L Ch R = 1 ,7268.8  ,607.9,587.5,567.1
XS GIS Cut Line= 4
     1829909.488      571952.722      1829896.09      572272.046
     1830049.967      572854.922     1830103.762      573223.319
#Sta/Elev= 30
       0   867.3   164.6  781.61   261.5  740.29   309.9  722.48   348.8  710.36
   397.4  699.55   465.4  695.16   484.9   692.3   504.4  687.77   541.3  675.09
     553  673.81   556.3  673.88   650.2  684.34   689.1  696.84   737.7   705.4
   786.3   718.8     796  723.11   805.8  731.45   834.9  769.98   844.7  777.84
   873.8  789.91   893.3  795.86   932.2  802.37   971.4  811.92  1020.4  827.62
    1089  846.63  1167.4  856.22  1226.2  868.44  1265.4  870.58  1294.8  869.67
#Mann= 3 , 0 , 0
       0      .1       0   541.3    .045       0   556.3     .08       0
Bank Sta=541.3,556.3
XS Rating Curve= 0 ,0
Exp/Cntr=0.3,0.1

Type RM Length L Ch R = 1 ,6681.1  ,663.1,669,674.2
XS GIS Cut Line= 4
     1829294.874      572297.248     1829451.716      572749.916
     1829913.954      572955.355     1830079.688       573343.78
#Sta/Elev= 30
       0  843.31    39.1  831.09    68.4   824.8     176   817.1   244.4  807.88
   254.2  805.62   283.5  795.56     352  768.29   371.5  762.96   410.6  755.57
   479.1   736.1   566.6  701.44   595.8  692.08     625  684.54   644.4  681.08
   712.5  678.36   735.7  673.65   741.7   672.4   750.7  672.56   790.4  683.24
   887.6  716.15   955.7  742.17   965.4  747.19   984.9  760.72  1092.9  797.58
    1142  812.04  1181.3  822.05  1230.4  831.79  1318.8  846.29  1407.2  874.66
#Mann= 3 , 0 , 0
       0     .08       0   735.7    .045       0   750.7     .08       0
Bank Sta=735.7,750.7
XS Rating Curve= 0 ,0
Exp/Cntr=0.3,0.1

Type RM Length L Ch R = 1 ,6011.8  ,272.1,269.9,268.3
XS GIS Cut Line= 5
      1828903.06      572709.303     1829111.477      573167.819
     1829453.876      573426.852     1829847.044      573751.144
     1830780.669      574415.379
#Sta/Elev= 30
       0  952.16   106.5  912.55   222.8  825.39   348.7  764.14   426.2  730.96
   484.3  712.63   679.6  671.78   689.1  670.74   694.6  671.15   776.9  684.13
   884.2  710.31   913.5  724.62  1050.6  808.83    1129  837.67    1276  825.24
  1315.2  826.74  1442.7  843.77  1530.8  861.38  1638.5  917.52  1746.2  946.22
    1805   932.9  1981.3  866.52    2089  836.19  2118.4  839.23  2177.2  855.82
  2255.5  863.42  2392.6  913.03    2422   912.5  2480.7   901.4  2588.5  907.03
#Mann= 3 , 0 , 0
       0     .08       0   679.6    .045       0   694.6     .08       0
Bank Sta=679.6,694.6
XS Rating Curve= 0 ,0
Exp/Cntr=0.3,0.1

Type RM Length L Ch R = 1 ,5742    ,360.2,364.4,368.6
XS GIS Cut Line= 4
       1828861.7       572824.19      1828935.39      573390.915
     1829426.658      573682.699     1830921.359      574729.652
#Sta/Elev= 30
       0  932.18    29.1  923.81    87.2  893.86   213.1  818.49   261.5  808.58
   455.3  752.99   542.4  722.84   774.9  670.91   784.6  668.87   794.2  668.98
   949.2  682.25  1104.1  741.53  1133.2  742.13  1182.1  748.64  1270.4  733.41
    1290  741.65  1368.5  792.62  1486.3  823.62  1682.5  893.83  1780.6   875.6
  1927.8  825.68    2075  791.32    2124  776.68  2173.1  769.32  2212.3  775.92
  2271.2   775.6  2467.4  790.89  2683.2  818.88  2869.7  861.31  2967.8  901.44
#Mann= 3 , 0 , 0
       0      .1       0   774.9    .045       0   794.2     .08       0
Bank Sta=774.9,794.2
XS Rating Curve= 0 ,0
Exp/Cntr=0.3,0.1

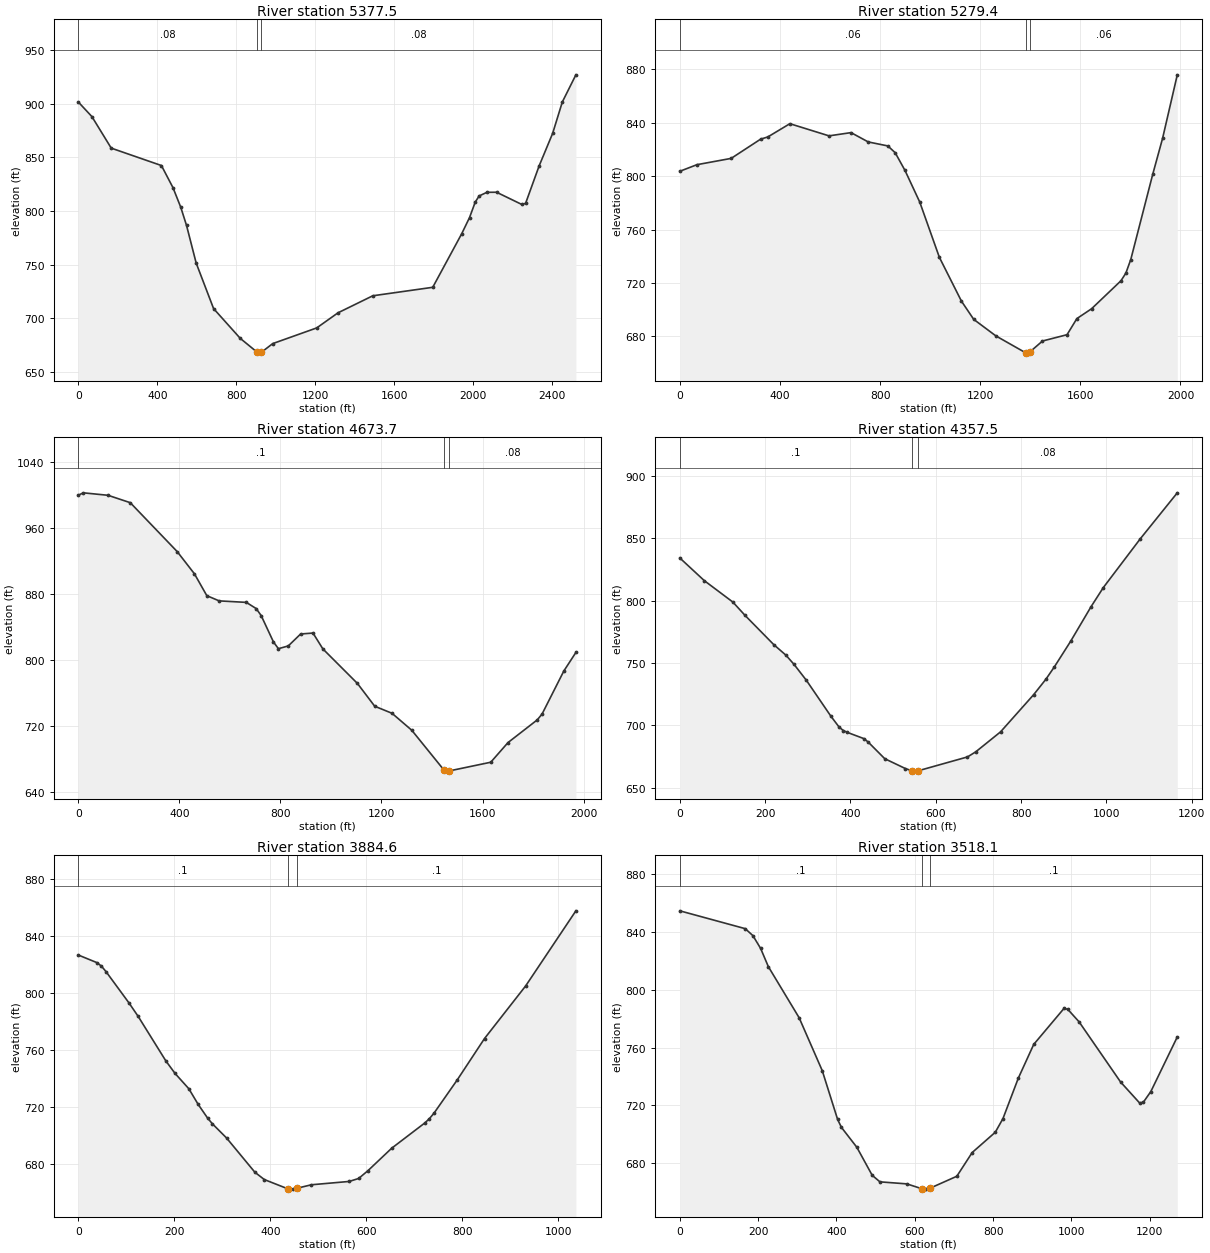
Type RM Length L Ch R = 1 ,5377.5  ,100,98.2,97.8
XS GIS Cut Line= 4
     1828807.784      572884.968     1828674.963      573566.377
     1829018.815      573877.258     1829565.897      575123.995
#Sta/Elev= 30
       0  901.65    68.4   888.1   166.2   858.7   420.4  842.45   479.1  821.72
   518.2  803.57   547.6   786.5   596.4  751.39   684.5  708.93   819.8  681.09
   906.7  667.99   916.4  667.35     926  668.04     984  676.24  1206.8  690.88
  1314.5  704.97  1490.8  720.88  1794.4  728.79  1941.4   778.9  1980.6  793.85
  2009.9  808.44  2029.5  814.08  2068.7  817.45  2117.7  817.53    2245  806.16
  2264.6  807.14  2333.2  842.14  2401.7  872.53  2450.7  901.79  2519.3  927.12
#Mann= 3 , 0 , 0
       0     .08       0   906.7    .045       0     926     .08       0
Bank Sta=906.7,926
XS Rating Curve= 0 ,0
Exp/Cntr=0.3,0.1

Type RM Length L Ch R = 1 ,5279.4  ,610,605.4,599.4
XS GIS Cut Line= 5
     1828666.728      572450.307      1828721.44      573132.091
     1828595.829      573605.944     1828930.261      573923.419
     1828920.924      574275.405
#Sta/Elev= 30
       0  803.65    68.4   808.6   205.2  813.32   322.4  827.69   351.8  829.42
   439.7  839.33     596  830.21     684  832.64   752.6  825.66     831  822.66
   860.4  817.58   899.7  804.25   958.5  780.59  1036.9  739.15  1125.2  706.25
  1174.2  692.62  1262.5  680.25  1383.4  667.37    1390  667.31  1398.4  668.19
  1448.9  676.39    1547  681.13  1586.3  693.21  1645.1   700.6  1762.5  721.59
    1782  727.31  1801.6   737.5  1889.6   801.6  1928.7  828.35  1987.4  875.97
#Mann= 3 , 0 , 0
       0     .06       0  1383.4    .045       0  1398.4     .06       0
Bank Sta=1383.4,1398.4
XS Rating Curve= 0 ,0
Exp/Cntr=0.3,0.1

Type RM Length L Ch R = 1 ,4673.7  ,321.9,316.2,310.5
XS GIS Cut Line= 4
     1827591.894      572706.362     1828099.912      573924.539
     1828498.509       574110.44     1828655.938      574249.446
#Sta/Elev= 30
       0  999.65    19.6 1002.47   117.3  999.48   205.3  990.54   391.1  931.34
   459.5  904.38   508.4  877.98   557.3  871.67   664.8  869.85   703.9  862.36
   723.5  853.94   772.4  821.88   791.9  813.79     831  817.15   879.9  831.59
   928.8  832.73   967.9  813.54  1104.8  771.71  1173.2  744.13  1241.6  735.62
  1319.9  715.07  1446.9  667.07  1456.7  665.58  1466.5  665.72  1632.6  676.34
    1701  700.16    1817  727.69    1836   734.8    1922  786.79  1969.7  809.25
#Mann= 3 , 0 , 0
       0      .1       0  1446.9    .045       0  1466.5     .08       0
Bank Sta=1446.9,1466.5
XS Rating Curve= 0 ,0
Exp/Cntr=0.3,0.1

Type RM Length L Ch R = 1 ,4357.5  ,467.4,472.9,478.4
XS GIS Cut Line= 4
     1827634.786      574227.291     1827977.653      574261.169
     1828418.119      574333.185     1828752.739      574503.155
#Sta/Elev= 30
       0  834.18    57.4  815.99   124.4   798.8   153.1  788.06   220.1  764.74
   248.8  756.21     268  748.76   296.7  736.08   354.2  707.28   373.6   698.5
   383.4   695.8     393  694.28   431.9  689.28   441.6  686.56   480.4  673.23
   528.9  665.31   544.5  663.49   548.3  663.26   559.5  663.61   674.4  674.65
   693.8  678.74     752  694.78   829.4  724.52   858.2  736.95   877.5  746.57
     916  767.26   964.1  795.13   992.9  810.48  1079.6  849.61  1166.2   886.4
#Mann= 3 , 0 , 0
       0      .1       0   544.5    .045       0   559.5     .08       0
Bank Sta=544.5,559.5
XS Rating Curve= 0 ,0
Exp/Cntr=0.3,0.1

Type RM Length L Ch R = 1 ,3884.6  ,359.8,366.6,373.5
XS GIS Cut Line= 4
      1827773.33      574416.924     1827893.914      574612.873
     1828373.599      574816.149     1828657.612      574785.375
#Sta/Elev= 30
       0  826.85    38.4  821.57    47.9  819.12    57.5  815.26   105.4  793.26
   124.6  783.79   182.2  752.61   201.3  743.85   230.1  733.07   249.7  722.02
   269.4   712.4   279.2  708.47   308.7  698.54   367.7   674.5   387.4  669.36
   436.5  662.85   446.3  662.64   456.2  663.31   485.6   665.7   564.3  668.03
     584  670.12   603.6  675.65   652.8  691.33   721.6  708.99   731.4  712.07
   741.2  716.01   789.2  739.14   846.3   768.3     932  805.19  1036.7  857.89
#Mann= 3 , 0 , 0
       0      .1       0   436.5    .045       0   456.2      .1       0
Bank Sta=436.5,456.2
XS Rating Curve= 0 ,0
Exp/Cntr=0.3,0.1

Type RM Length L Ch R = 1 ,3518.1  ,463,488.3,513.6
XS GIS Cut Line= 4
     1827649.397      574490.614     1827830.273      574872.463
     1828181.976      575200.719     1828300.885      575547.398
#Sta/Elev= 30
       0  854.65     167  842.31   186.7  837.46   206.4  828.59     226  816.04
   304.6  780.69   363.6   744.1   402.9   710.3   412.7  704.78     452  691.03
   491.2  671.65   510.9  667.12   579.6  665.71   618.9  662.27   628.7  662.08
   638.5  662.68   707.2  670.98   746.5  687.41   805.4  701.43   825.1  710.93
   864.3  738.91   903.6  762.24   980.8   787.1   990.4  786.53  1019.4  777.84
  1125.4  736.19  1173.7  721.76  1183.3  722.15  1202.6  729.62  1270.1  767.39
#Mann= 3 , 0 , 0
       0      .1       0   618.9    .045       0   638.5      .1       0
Bank Sta=618.9,638.5
XS Rating Curve= 0 ,0
Exp/Cntr=0.3,0.1

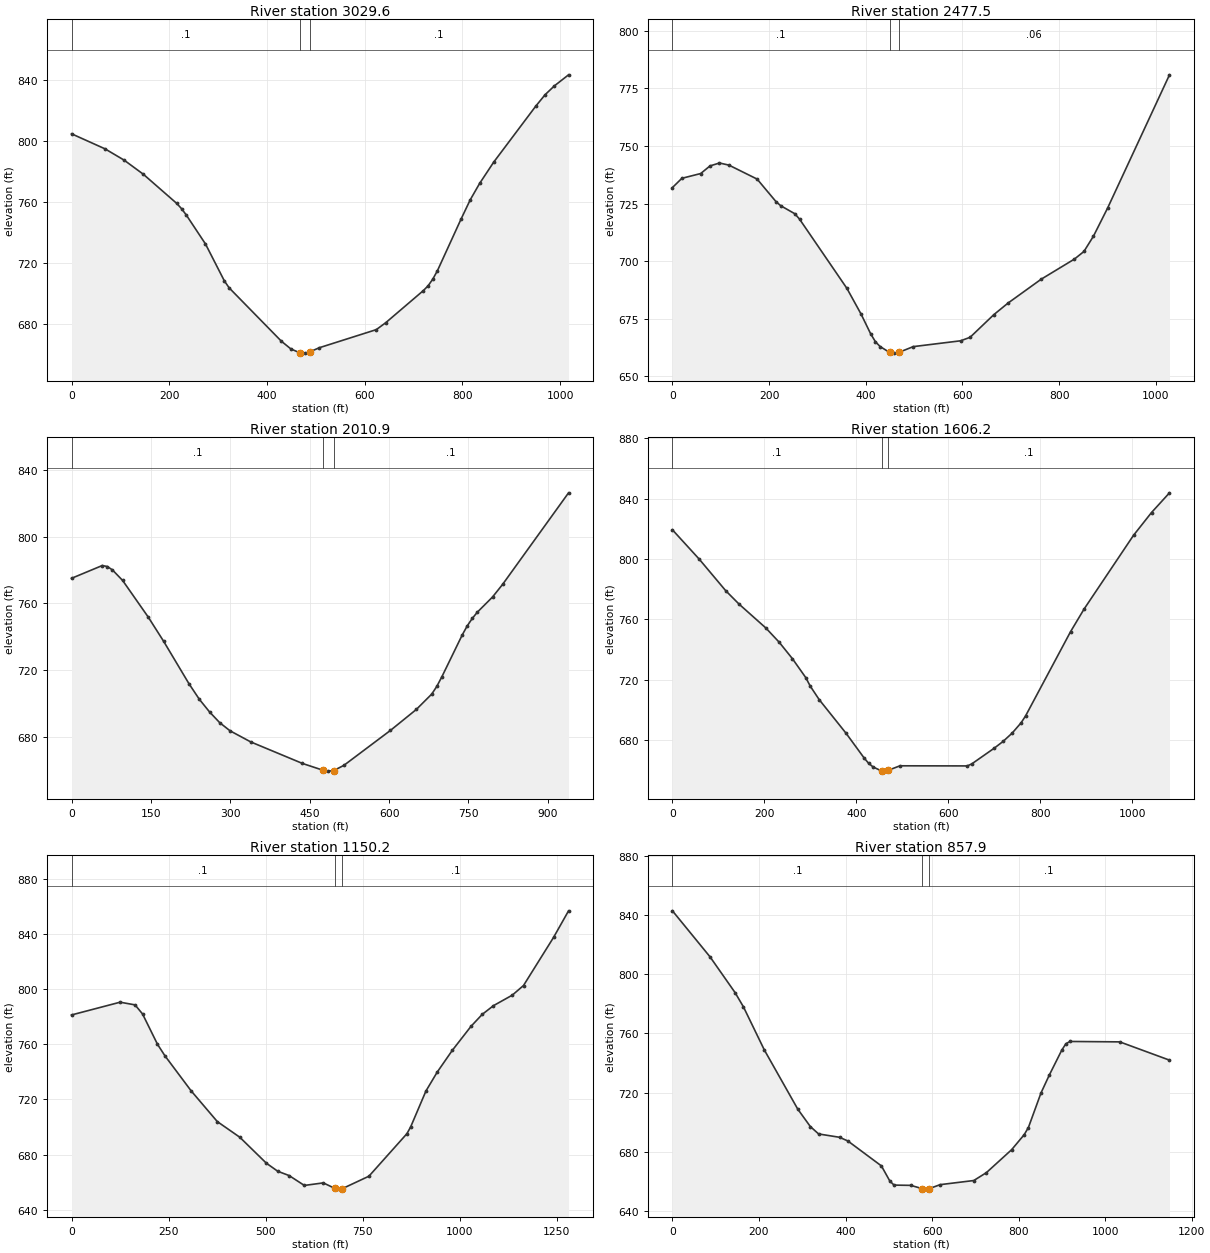
Type RM Length L Ch R = 1 ,3029.6  ,554.7,551.9,549.2
XS GIS Cut Line= 4
     1827498.667      574547.556     1827563.983      574813.846
     1827456.797       575197.37     1827503.691      575539.024
#Sta/Elev= 30
       0  804.56    68.6  794.72   107.7  787.34   146.9  778.15   215.4  759.06
   225.2  755.65     235  751.46   274.2  732.58     313  708.36   322.8  703.86
   429.6  669.04     449  664.01   468.4  661.34   478.2  661.28   487.3  662.07
   507.3  664.82   623.8  676.63   643.3   681.2   720.3  702.18   729.9  705.29
   739.5  709.65     749  715.18   796.9  748.59   816.1  761.45   835.2  772.09
     864     786   950.2  822.62   969.4  830.12   988.5  835.91  1017.3  843.07
#Mann= 3 , 0 , 0
       0      .1       0   468.4    .045       0   487.3      .1       0
Bank Sta=468.4,487.3
XS Rating Curve= 0 ,0
Exp/Cntr=0.3,0.1

Type RM Length L Ch R = 1 ,2477.5  ,463.8,466.6,469.3
XS GIS Cut Line= 4
     1826974.462      574396.826     1827026.666       574634.45
     1826954.364      575148.801     1826996.369      575410.957
#Sta/Elev= 30
       0  731.92    19.5  735.93    58.4     738    77.8  741.32    97.3  742.57
   116.8  741.66   175.2  735.59   214.1  725.84   223.8  724.06   253.1  720.56
   262.9  718.23   360.9  688.18   390.3  676.98   409.9  668.52   419.7  665.08
   429.5  662.95   449.1   660.4   458.9  660.08   468.7  660.43   498.1   662.9
   596.1  665.43   615.7  666.94   664.7  676.75   694.1  681.78   762.7  692.14
   831.5  700.88   851.2  704.18   870.9  710.82   900.4  723.11  1028.2  780.83
#Mann= 3 , 0 , 0
       0      .1       0   449.1    .045       0   468.7     .06       0
Bank Sta=449.1,468.7
XS Rating Curve= 0 ,0
Exp/Cntr=0.3,0.1

Type RM Length L Ch R = 1 ,2010.9  ,413,404.4,395.7
XS GIS Cut Line= 4
     1826766.789      574393.477     1826611.035      574626.271
     1826507.199      575003.096     1826567.491      575264.361
#Sta/Elev= 30
       0  775.03      58  782.66    67.6  782.09    77.3  780.06    96.6  773.74
   144.9   751.9   173.8  737.54   222.1  711.98   241.5  702.77   260.8  695.22
   280.1  688.77   299.6  683.93   338.7   677.3   436.4  664.44   475.5  660.36
   485.3  659.86   495.1  660.14   514.6   663.3   602.6  684.19   651.4  696.68
   680.5  705.85   690.1  710.44   699.7   716.2     738  741.07   747.6  746.59
   757.2  751.08   766.7  754.79   795.4  763.85   814.6  771.45   939.1   826.1
#Mann= 3 , 0 , 0
       0      .1       0   475.5    .045       0   495.1      .1       0
Bank Sta=475.5,495.1
XS Rating Curve= 0 ,0
Exp/Cntr=0.3,0.1

Type RM Length L Ch R = 1 ,1606.2  ,461.4,456.1,450.9
XS GIS Cut Line= 4
     1826327.998      574308.063     1826167.219      574549.231
     1826230.127      575082.094     1826398.339      575272.735
#Sta/Elev= 30
       0  819.25      58   799.9   115.9  778.88   144.9     770   202.9  754.25
   231.9  744.82   260.9  733.83   289.8  721.34   299.6  715.66   319.1   706.7
   377.6  684.38   416.7  668.06   426.4  664.57   436.2   662.1   454.6  659.46
   455.7  659.34   469.6  659.94   494.7  662.87     641  662.79   650.8  664.14
   699.6  674.55   719.1   679.1   738.6  684.55   758.1   691.4   767.9  696.03
   865.5  751.74   894.9  766.74  1002.4  815.61  1041.5   830.7  1080.6  843.77
#Mann= 3 , 0 , 0
       0      .1       0   454.6    .045       0   469.6      .1       0
Bank Sta=454.6,469.6
XS Rating Curve= 0 ,0
Exp/Cntr=0.3,0.1

Type RM Length L Ch R = 1 ,1150.2  ,286.3,291.9,297.5
XS GIS Cut Line= 4
     1825865.331       574260.07     1825698.282      574659.766
      1825862.41      575110.281     1826149.121      575339.973
#Sta/Elev= 30
       0  781.17   125.2  790.41   163.6  788.46   182.9   781.9   221.4  759.93
   240.7  751.53     308  726.22   375.4  703.94   433.2  692.63   501.7  673.82
     531  667.97   560.4  664.83   599.6  657.68   648.5  659.53   677.8  655.58
   687.6  655.01   697.4  655.36   765.9  664.37   863.8  695.19   873.5  700.16
   912.7  726.07   941.7  739.74   980.4  755.45  1028.7   772.9  1057.7  781.59
  1086.7  787.91    1135   795.5    1164   802.5  1241.4  837.35    1280  856.59
#Mann= 3 , 0 , 0
       0      .1       0   677.8    .045       0   697.4      .1       0
Bank Sta=677.8,697.4
XS Rating Curve= 0 ,0
Exp/Cntr=0.3,0.1

Type RM Length L Ch R = 1 ,857.9   ,421.4,425.1,428.8
XS GIS Cut Line= 4
     1825552.694      574367.473      1825490.61      574807.147
     1825534.154      575212.443      1825698.19      575459.998
#Sta/Elev= 30
       0  842.82    86.9  811.71   144.8  787.53   164.1   777.9   212.4  748.76
   289.6   708.8   318.6  697.04   337.8  692.02   386.1  689.77   405.4  687.27
   482.9  670.42   502.3  660.24     512  657.46   550.8  657.27   577.3  655.05
   589.6  654.73   592.3  654.95   618.7  657.76   696.4  660.55   725.5  665.87
   783.7  681.34   812.8  691.51   822.6  696.38   851.7  719.74   870.8  731.78
   899.6  748.61   909.1  752.96   918.7  754.53  1033.7  754.25  1148.6   741.9
#Mann= 3 , 0 , 0
       0      .1       0   577.3    .045       0   592.3      .1       0
Bank Sta=577.3,592.3
XS Rating Curve= 0 ,0
Exp/Cntr=0.3,0.1