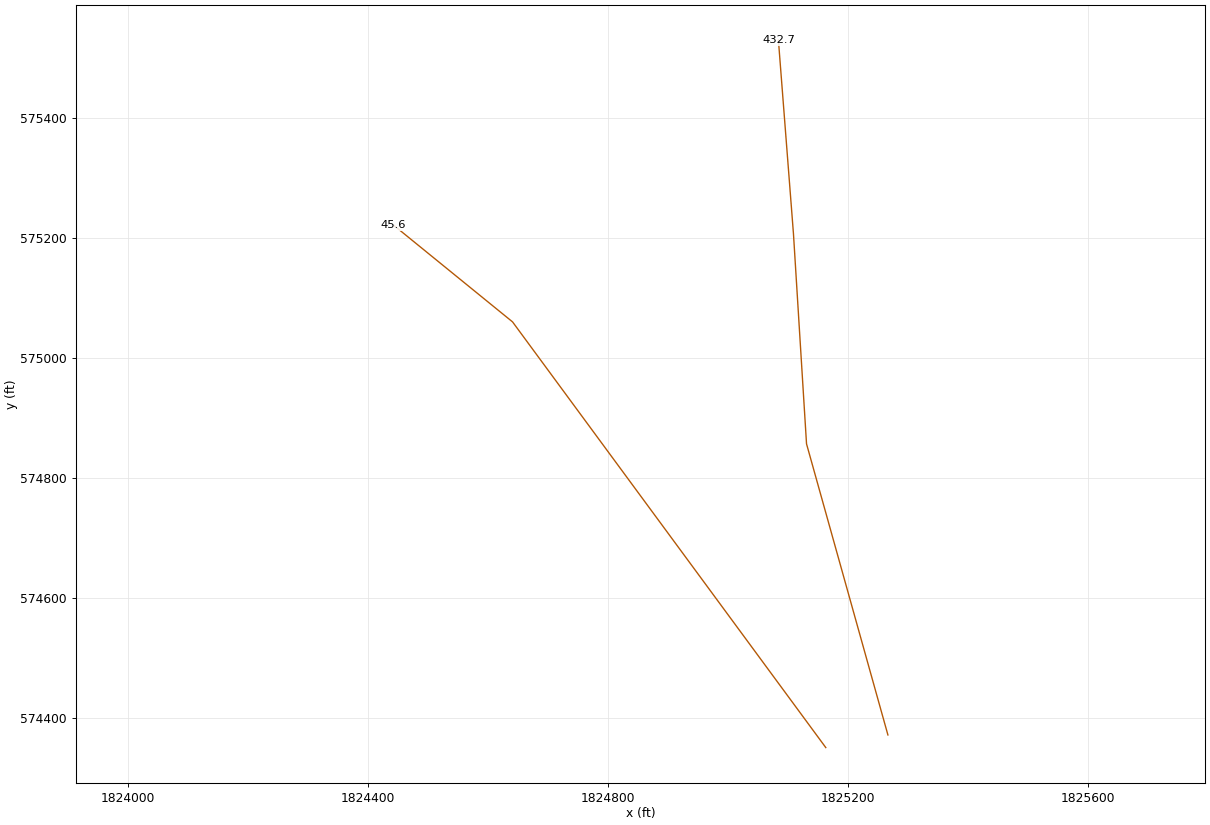
HEC-RAS study GreenCrk.prj: GreenCrk

--- GreenCrk.g01 (geometry) --- (continued)

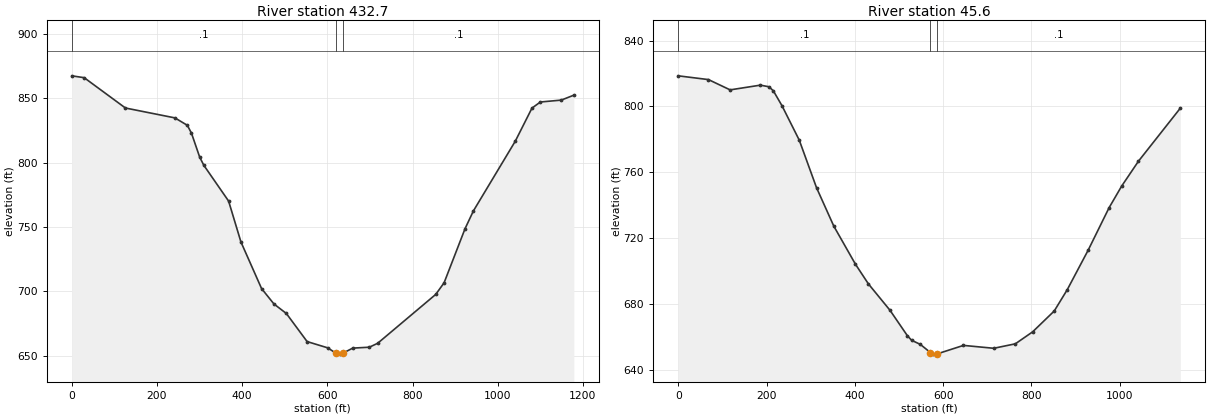
Type RM Length L Ch R = 1 ,432.7   ,377,387,396.7
XS GIS Cut Line= 4
     1825266.183      574372.214     1825130.533       574857.39
      1825108.76      575207.418     1825083.639       575530.65
#Sta/Elev= 30
       0  867.45    29.1  866.01     126  842.43   242.2  834.75   271.3  828.98
     281   822.9   300.3  804.26     310  797.91   368.2  770.08   397.2  738.26
   445.6  702.06   474.7  690.08   503.8   682.7   552.5  660.87   601.2  655.96
   620.7  651.68   630.4  651.11   636.2   651.8   659.6  655.78   698.6  656.49
   718.1  659.53   854.5  697.55   874.1  706.58   923.3  748.65   942.9  762.44
  1041.2  816.63  1080.4  842.36  1100.1   847.1  1149.2  848.58  1178.7  852.41
#Mann= 3 , 0 , 0
       0      .1       0   620.7    .045       0   636.2      .1       0
Bank Sta=620.7,636.2
XS Rating Curve= 0 ,0
Exp/Cntr=0.3,0.1

Type RM Length L Ch R = 1 ,45.6    ,33.5,45.6,58.2
XS GIS Cut Line= 3
     1825162.626      574351.155     1824640.505      575060.725
     1824441.731      575222.287
#Sta/Elev= 30
       0   818.6    68.5  816.31   117.5  810.07     186  812.94   205.6  811.95
   215.4  809.49   234.9  800.48   274.1  779.54   313.2  750.66   352.4  727.28
   401.3  704.22   430.7  692.24   479.6  676.22   518.8  660.84   528.6  657.98
   548.2  655.52   571.1  650.57   577.5  649.59   586.1  649.71     646  654.89
   714.6  653.14   763.5  655.85   802.7  663.13   851.6  675.79     881   688.7
   928.4  712.71   975.8  738.51  1004.3  751.65  1042.2  766.71  1137.1  798.95
#Mann= 3 , 0 , 0
       0      .1       0   571.1    .045       0   586.1      .1       0
Bank Sta=571.1,586.1
XS Rating Curve= 0 ,0
Exp/Cntr=0.3,0.1

Chan Stop Cuts=-1
Use User Specified Reach Order=0
Composite Channel Slope=5